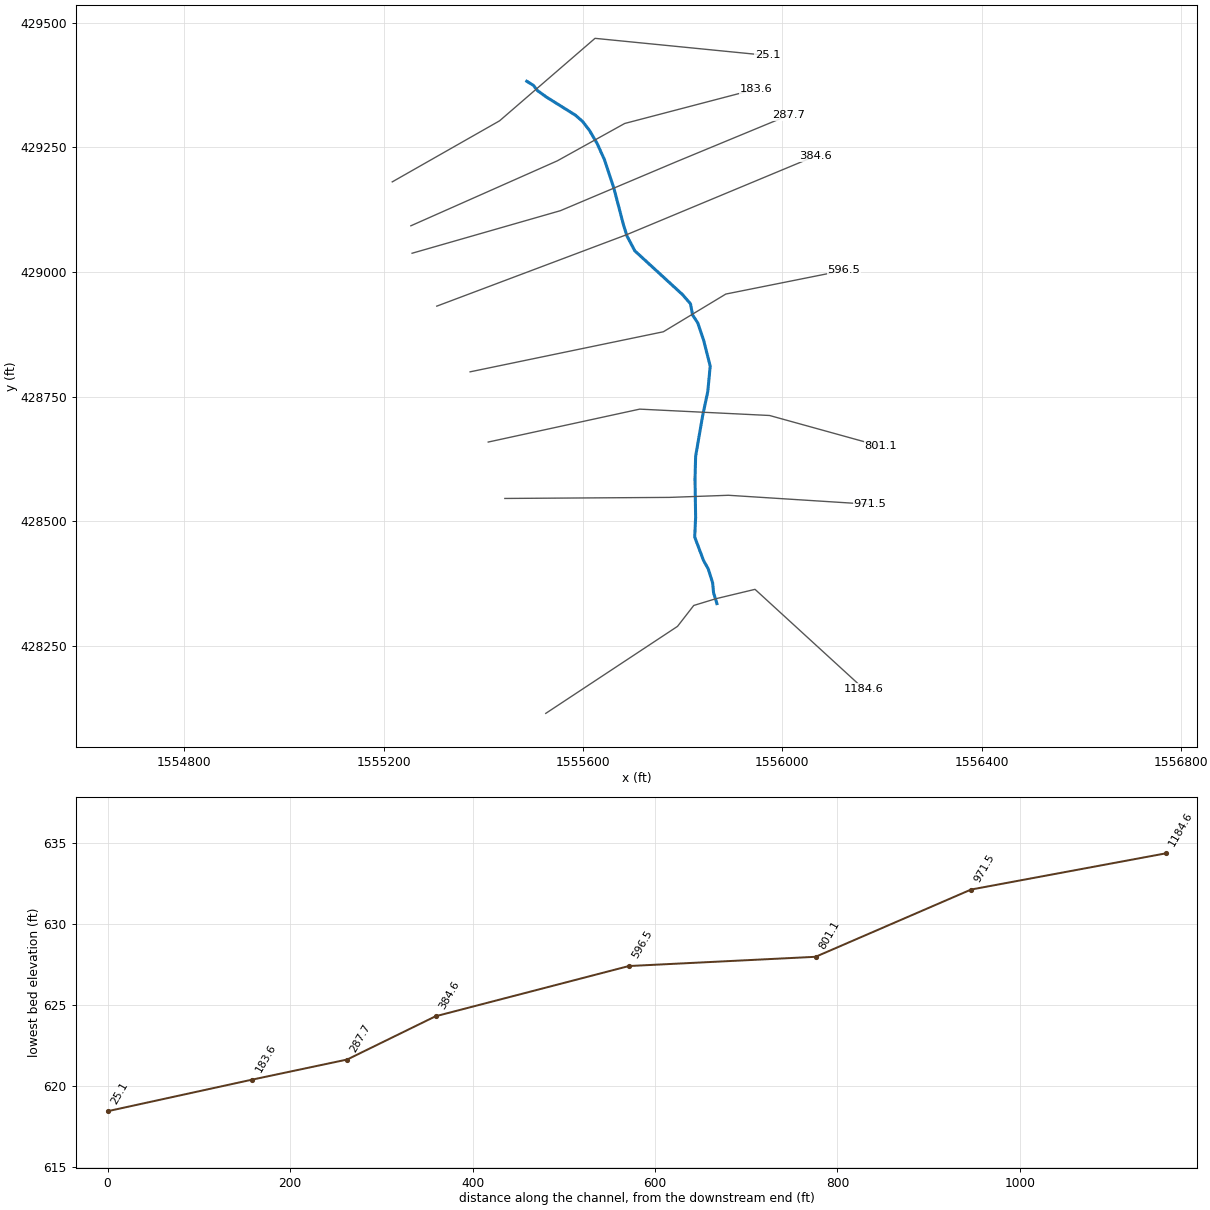
--- NP68.prj (project) ---

Proj Title=NP68
Current Plan=p01
Default Exp/Contr=0,0
English Units
Geom File=g01
Flow File=f01
Plan File=p01
BEGIN DESCRIPTION:
END DESCRIPTION:
DSS Export Rating Curves= 0
DSS Export Rating Curve Sorted= 0
DSS Export Volume Flow Curves= 0
DXF OffsetX= 0
DXF OffsetY= 0
DXF ScaleX= 0
DXF ScaleY= 0

--- NP68.p01 (plan) ---

Plan Title=Floodplain
Program Version=4.00
Geom File=g01
Flow File=f01
K Sum by GR=0
Std Step Tol=0.01
Critical Tol=0.01
Num of Std Step Trials=20
Max Error Tol=0.3
Flow Tol Ratio=0.001
Split Flow NTrial=30
Split Flow Tol=0.02
Split Flow Ratio=0.02
Log Output Level=0
Friction Slope Method=1
Unsteady Friction Slope Method=2
Unsteady Bridges Friction Slope Method=1
Global Log Level=0
CheckData=False
Run HTab=0
Run UNet=0
Run PostProcess=0
UNET Theta=0
UNET Theta Warmup=0
UNET ZTol=0
UNET ZSATol=0
UNET MxIter=0
UNET MaxInSteps=0
UNET DtIC=0
UNET DtMin=0
UNET MaxCRTS=0
UNET WFStab=0
UNET SFStab=0
UNET WFX=0
UNET SFX=0
UNET DSS MLevel=0
UNET DZMax Abort=0
UNET Convert EG Bridges=0
UNET Use Existing IB Tables=0
UNET Froude Limit=0
UNET Froude Power=0
Write IC File=0
Echo Input=False
Echo Output=False
Write Detailed=0

--- NP68.f01 (steady flow) ---

Flow Title=NFF Regression Equation
Program Version=4.00
Number of Profiles=1
Profile Names=P100yr
River Rch & RM=NP68,Main      ,1184.6
     402
River Rch & RM=NP68,Main      ,287.7
     407
Boundary for River Rch & Prof#=NP68,Main      ,1
Up Type=0
Dn Type=3
Dn Slope=0.017253

--- NP68.g01 (geometry) ---

Geom Title=USGS 10m DEM
Program Version=4.00

River Reach=NP68            ,Main
Reach XY= 30
     1555868.764      428334.814     1555862.059      428356.758
      1555860.23      428376.263     1555851.697      428403.692
     1555841.944      428421.369     1555824.268      428468.303
     1555826.096      428507.923     1555824.877      428584.115
     1555826.096       428630.44     1555840.116      428711.509
     1555850.478      428760.272     1555855.354      428811.473
     1555841.944      428863.893     1555830.363      428898.027
     1555820.001      428913.875     1555815.734      428936.428
     1555799.886      428954.714     1555704.189      429042.488
     1555688.341      429072.355     1555681.636      429093.689
     1555662.131      429168.052     1555643.235      429225.349
     1555628.606      429257.655     1555613.368      429283.865
     1555599.348      429302.151     1555584.719      429314.951
     1555526.203      429351.524     1555508.527      429364.324
     1555500.603      429374.686     1555487.309      429382.872

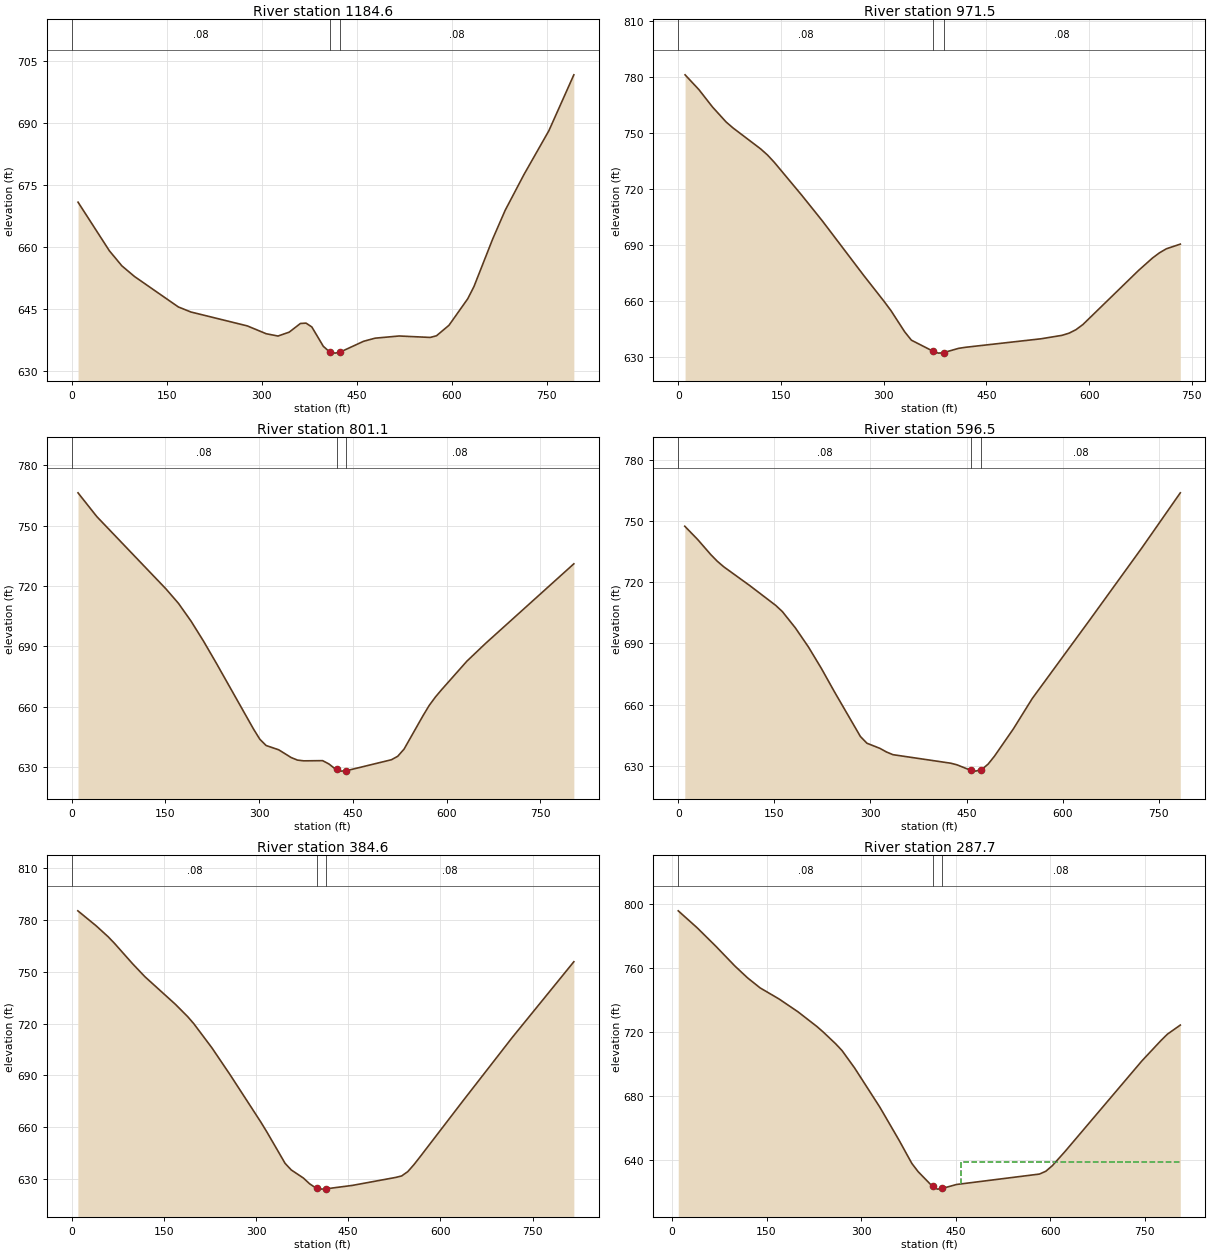
Type RM Length L Ch R = 1 ,1184.6  ,219.1,213.1,208.5
XS GIS Cut Line= 6
     1555525.406      428114.569     1555789.744      428289.132
     1555822.312      428331.076     1555865.842      428344.377
     1555945.255      428363.435     1556163.327      428163.816
#Sta/Elev= 30
     9.9  670.88    59.4  659.11    79.2  655.45      99  652.89   168.3  645.51
   188.1  644.29   277.2  640.92   306.9  639.03   325.6  638.47   343.3  639.41
     361  641.51   369.9  641.59     379  640.67   397.2  635.97   407.9  634.53
   415.4  634.33   422.9  634.52   460.8   637.2   478.9  637.95   516.8  638.48
     566  638.13   575.9  638.54   595.6  641.08   625.2   647.5     635  650.45
   664.6  661.98   684.3  668.92   713.9  677.56   753.3  688.19   792.7  701.72
#Mann= 3 , 0 , 0
       0     .08       0   407.9    .045       0   422.9     .08       0
Bank Sta=407.9,422.9
XS Rating Curve= 0 ,0
Exp/Cntr=0.3,0.1

Type RM Length L Ch R = 1 ,971.5   ,172.3,170.4,168.5
XS GIS Cut Line= 4
     1555443.282      428545.793     1555773.939      428547.919
     1555891.955      428552.172     1556175.831      428534.098
#Sta/Elev= 30
      10  780.97    30.1   773.1    50.1  763.73    70.1  755.68    80.2   752.5
   120.2  741.39   130.3  738.11   140.3  734.17   180.4  716.55   210.4  702.85
   270.5  673.84   300.6  659.78   310.6  654.87   330.7   643.5   340.5  639.03
   372.4  633.06   379.9   632.1   387.4  632.35   409.4  634.65   419.2  635.21
     530  639.78   560.5  641.62   570.7  642.77   580.8  644.64     591  647.41
   672.3  676.36   692.6  682.98   702.7  685.74   712.9  687.93   733.2  690.41
#Mann= 3 , 0 , 0
       0     .08       0   372.4    .045       0   387.4     .08       0
Bank Sta=372.4,387.4
XS Rating Curve= 0 ,0
Exp/Cntr=0.3,0.1

Type RM Length L Ch R = 1 ,801.1   ,191.1,204.6,218.2
XS GIS Cut Line= 4
     1555409.943      428658.955     1555713.923      428725.015
     1555974.409      428712.256     1556197.634      428650.457
#Sta/Elev= 30
      10   766.3    40.1  754.48   150.5  718.62   170.6  711.42   190.7   702.6
   210.7  692.65   230.8  681.91     291   648.8     301  643.81   311.1  640.67
   331.1  638.57   351.2  634.69   361.2  633.43   371.3  633.06   401.4  633.16
   411.4  631.54   421.4  629.13   423.9  628.84   431.4  627.95   438.9  628.11
   511.7  633.62   521.7  635.34   531.8   638.9   561.8  655.33   571.9  660.55
   581.9  664.77     592  668.48   632.3   682.6   662.5  691.52   803.5  731.01
#Mann= 3 , 0 , 0
       0     .08       0   423.9    .045       0   438.9     .08       0
Bank Sta=423.9,438.9
XS Rating Curve= 0 ,0
Exp/Cntr=0.3,0.1

Type RM Length L Ch R = 1 ,596.5   ,216.1,211.9,208.4
XS GIS Cut Line= 4
     1555373.602      428799.852     1555761.371      428880.243
     1555886.686      428955.905     1556123.131      429003.194
#Sta/Elev= 30
    10.2  747.38    30.5  740.82    50.8  733.48    60.9  730.24    71.1  727.49
   111.7  718.28   152.3  708.55   162.5  705.56   182.8  697.56   203.1  688.26
   223.4   677.7   243.7  666.29   284.3  644.34   294.5  641.05   314.8  638.52
   324.9  636.77   335.1  635.44   425.3  631.26   435.1  630.46   456.8  627.73
   464.3  627.38   471.8  628.07   474.1  628.28   483.8   630.9   493.6  634.75
   522.9  648.04   552.4  662.93   642.9  701.77   723.2  736.64   783.5  763.75
#Mann= 3 , 0 , 0
       0     .08       0   456.8    .045       0   471.8     .08       0
Bank Sta=456.8,471.8
XS Rating Curve= 0 ,0
Exp/Cntr=0.3,0.1

Type RM Length L Ch R = 1 ,384.6   ,96,96.9,97
XS GIS Cut Line= 3
      1555306.72      428931.635     1555687.522      429074.959
      1556066.38      429232.755
#Sta/Elev= 30
     9.9  785.13    39.7  776.47    59.5  770.05    69.5  766.36    99.2  754.47
   119.1  747.04   168.7   731.1   188.6  724.01   198.5  719.96   228.3  705.86
     258  690.25   307.6  663.13   317.6  657.33   347.3  639.16   357.3  635.37
   377.1  630.68     387  627.41     397  625.03   399.4  624.85   406.9  624.28
   414.4  624.47   456.9  626.44     527  631.02     537  631.89     547   634.4
     557  638.43     567  642.96   637.1  675.42   717.2     712   817.3  755.71
#Mann= 3 , 0 , 0
       0     .08       0   399.4    .045       0   414.4     .08       0
Bank Sta=399.4,414.4
XS Rating Curve= 0 ,0
Exp/Cntr=0.3,0.1

Type RM Length L Ch R = 1 ,287.7   ,101.7,104.1,106.5
XS GIS Cut Line= 4
     1555257.183      429037.784     1555554.849      429123.201
     1555787.804       429221.56     1556012.995      429314.742
#Sta/Elev= 30
      10  795.85      40  785.24    69.9  773.58    99.9  761.28   119.9  753.89
   139.9  747.59   169.8  740.68   199.8  732.66   229.8  723.47   239.8  720.03
   259.7   712.6   269.7   708.4   289.7  697.48   329.9  672.83   360.3  652.18
   380.5   637.7   390.6   632.5   410.8  624.31   413.4  623.61   420.9  621.61
   428.4  622.01   451.3  624.51   582.9  631.04     593  632.81   603.2  636.24
   623.5  645.19   745.3  701.86   775.8  714.72   785.9  718.64   806.3  724.32
#Mann= 3 , 0 , 0
      10     .08       0   413.4    .045       0   428.4     .08       0
#XS Ineff= 2 , 0
                          458.83          638.61
Permanent Ineff=
       F       F
Bank Sta=413.4,428.4
XS Rating Curve= 0 ,0
Exp/Cntr=0.3,0.1

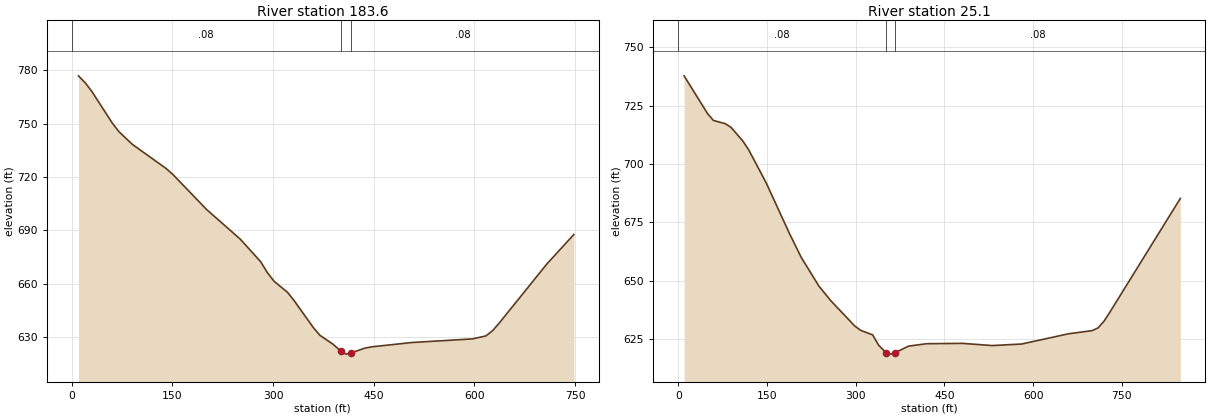
Type RM Length L Ch R = 1 ,183.6   ,153.9,158.5,163.1
XS GIS Cut Line= 4
     1555254.718      429092.854     1555548.571      429223.182
     1555683.817      429298.182     1555946.933      429367.035
#Sta/Elev= 30
      10  776.89    20.1  772.96    30.1  768.01    60.3  750.36    70.3  745.48
    90.4  738.31   140.6  724.77   150.7   721.4   200.9  701.71   251.1  685.03
   281.3  672.41   291.3  666.31   301.4  661.36   321.5  655.13   331.1  650.59
   360.1  635.22   369.8  630.94   389.1  626.01   400.9  622.12   408.4  620.37
   415.9  621.03   437.4  623.82   447.1  624.47   506.3  626.89     597  628.93
   617.1  630.63   627.2  633.62   637.3  638.01   707.8  671.03   748.1  687.65
#Mann= 3 , 0 , 0
       0     .08       0   400.9    .045       0   415.9     .08       0
Bank Sta=400.9,415.9
XS Rating Curve= 0 ,0
Exp/Cntr=0.3,0.1

Type RM Length L Ch R = 1 ,25.1    ,18.1,25.1,32.1
XS GIS Cut Line= 4
     1555217.387      429180.987     1555432.713      429303.478
     1555624.233      429468.989     1555970.609       429434.65
#Sta/Elev= 30
     9.9  737.81    49.5  721.64    59.5  718.67    79.3  717.31    89.2  715.73
     109  709.92   118.9  706.16   148.6  691.95   188.3  670.05   208.1  659.86
   237.8  647.63   257.9  641.35   298.4   630.5   308.5  628.61   328.7  626.69
   338.9  622.22   351.6  619.05   359.1  618.42   366.6  619.03   389.5  621.85
   419.9  622.89   480.6  623.04   530.7  622.09   580.4  622.75     660  627.15
   699.8   628.5   709.7  629.63   719.6  632.45   729.6  636.32   848.9  685.21
#Mann= 3 , 0 , 0
       0     .08       0   351.6    .045       0   366.6     .08       0
Bank Sta=351.6,366.6
XS Rating Curve= 0 ,0
Exp/Cntr=0.3,0.1

Chan Stop Cuts=-1
Use User Specified Reach Order=0